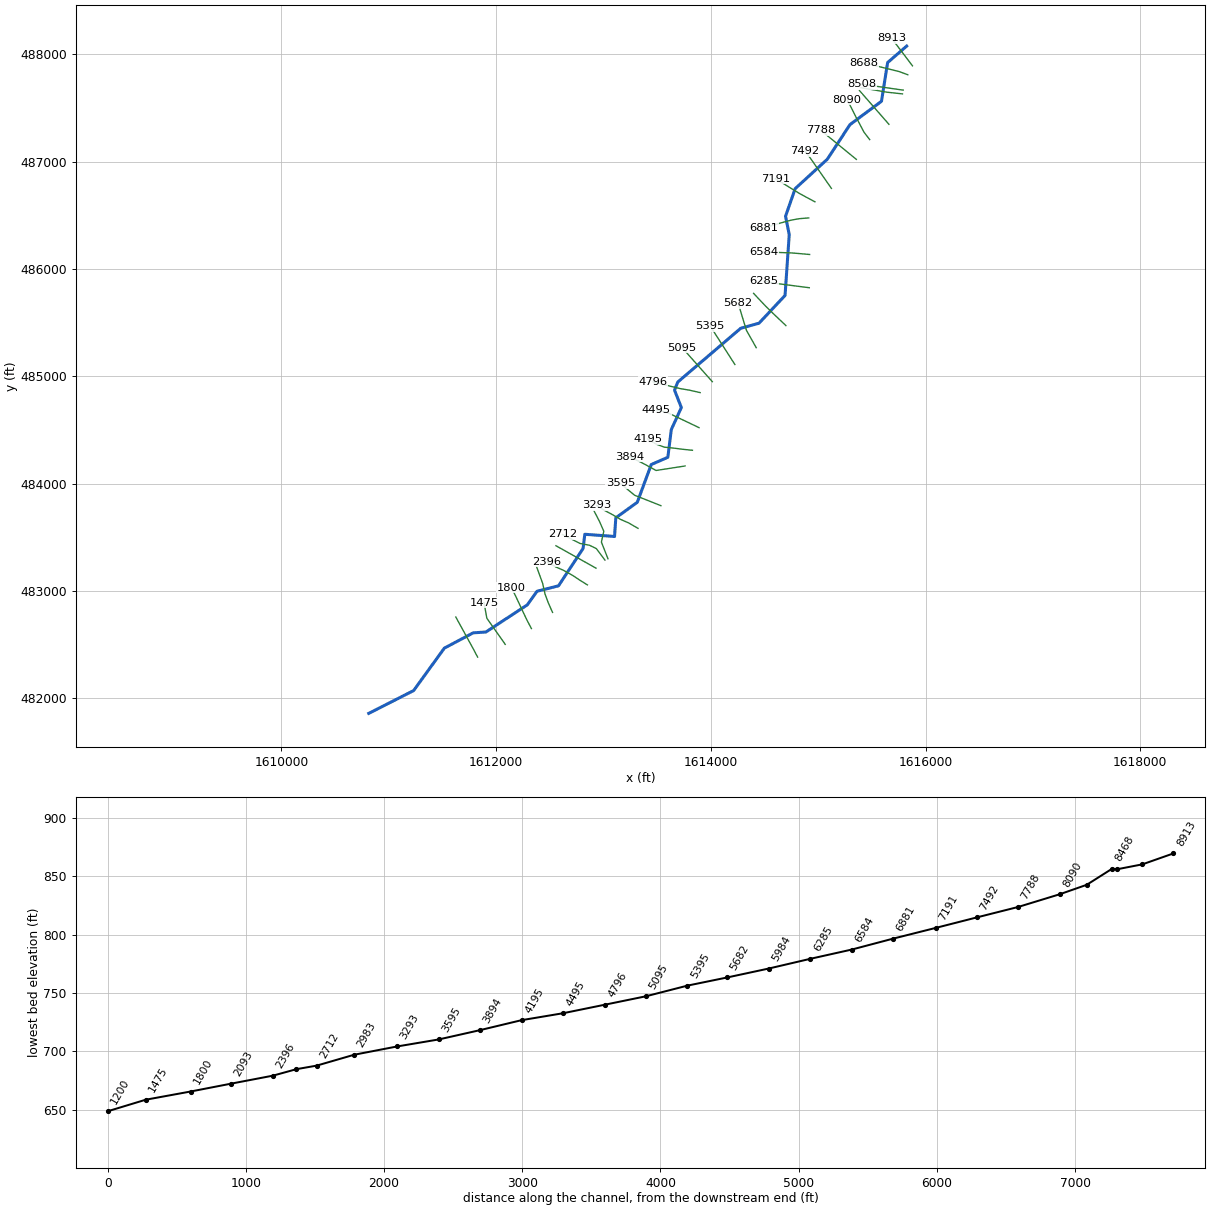
--- LtleTrbbCk.prj (project) ---

Proj Title=LtleTrbbCk
Current Plan=p01
Default Exp/Contr=0,0
English Units
Geom File=g01
Flow File=f01
Plan File=p01
BEGIN DESCRIPTION:
---------- MODELED AS PART OF WVEM CTP PROGRAM, 2025----------
Stream Name: Little Tribble Creek
Flood Zone: AFH
Marshall County, WV
HEC-RAS Version: RAS 6.6
Vertical Datum: NAVD88
Projection: NAD 1983 StatePlane West Virginia N FIPS 4701 (US Feet)
Terrain: 1-meter West Virginia FEMA R3 South Central (collected 2018-2019)
Land Use: 2024 NLCD
Hydrologic Method:
Duda et al., "Estimation of magnitude and frequency of floods for rural, unregulated streams in and near Virginia and West Virginia." September 8, 2025.
Additional Model Notes:
None
END DESCRIPTION:
DSS Export Rating Curves= 0
DSS Export Rating Curve Sorted= 0
DSS Export Volume Flow Curves= 0
DXF OffsetX= 0
DXF OffsetY= 0
DXF ScaleX= 0
DXF ScaleY= 0

--- LtleTrbbCk.p01 (plan) ---

Plan Title=Floodplain
Program Version=6.60
Short Identifier=Floodplain
Geom File=g01
Flow File=f01
Subcritical Flow
K Sum by GR= 0
Std Step Tol= 0.01
Critical Tol= 0.01
Num of Std Step Trials= 20
Max Error Tol= 0.3
Flow Tol Ratio= 0.001
Split Flow NTrial= 30
Split Flow Tol= 0.02
Split Flow Ratio= 0.02
Log Output Level= 0
Friction Slope Method= 1
Unsteady Friction Slope Method= 2
Unsteady Bridges Friction Slope Method= 1
Parabolic Critical Depth
Global Vel Dist= 0 , 0 , 0
Global Log Level= 0
CheckData=False
Encroach Param=-1 ,0,0, 0
Flow Ratio Tolerance=0.1
Flow Ratio Min Ratio=0.5
Flow Ratio Max Ratio=4
Flow Ratio Max Iterations= 10
Mapping Interval=1HOUR
Computation Time Step Use Courant=        0
Computation Time Step Use Time Series=    0
Computation Time Step Count To Double=0
Computation Time Step Max Doubling=0
Computation Time Step Max Halving=0
Computation Time Step Residence Courant=0
Run HTab= 0
Run UNet= 0
Run Sediment= 0
Run PostProcess= 0
Run WQNet= 0
Run RASMapper=-1
UNET Theta= 0
UNET Theta Warmup= 0
UNET ZTol= 0
UNET ZSATol= 0
UNET MxIter= 0
UNET Max Iter WO Improvement= 0
UNET MaxInSteps= 0
UNET DtIC= 0
UNET DtMin= 0
UNET MaxCRTS= 0
UNET WFStab= 0
UNET SFStab= 0
UNET WFX= 1
UNET SFX= 1
UNET Gravity=32.17405
UNET 1D Methodology=Finite Difference
UNET DSS MLevel= 1
UNET Pardiso=0
UNET DZMax Abort= 0
UNET Use Existing IB Tables= 0
UNET Froude Reduction=False
UNET Froude Limit= 0
UNET Froude Power= 0
UNET D1 Cores= 0
UNET WindReference=Eulerian
UNET WindDragFormulation=Hsu (1988)
UNET D2 Coriolis=0
UNET D2 Cores= 0
UNET D2 Theta= 1
UNET D2 Theta Warmup= 1
UNET D2 Z Tol= 0.01
UNET D2 Volume Tol= 0.01
UNET D2 Max Iterations= 20
UNET D2 Advanced Convergence=0
UNET D2 WS Max Tol=0.15
UNET D2 WS RMS Tol=0.002
UNET D2 WS Stall Tol=1
UNET D2 Equation= 0
UNET D2 RampUpFraction=0.1
UNET D2 TimeSlices= 1
UNET D2 Turbulence Formulation=Non-Conservative (original)
UNET D2 Eddy Viscosity=0.3
UNET D2 Transverse Eddy Viscosity=0.1
UNET D2 Smagorinsky Mixing=0
UNET D2 BCVolumeCheck=0
UNET D2 Cores=0
UNET D2 SolverType=PARDISO (Direct)
UNET D2 Minimum Iterations= 3
UNET D2 Maximum Iterations= 30
UNET D2 Restart Number= 10
UNET D2 Relaxation Coeff=1.3
UNET D2 SOR Precondition Iterations= 10
UNET D2 ILUT Maximum Fill= 8
UNET D2 ILUT Tolerance=1E-08
UNET D2 Convergence Tolerance=0.00001
PS Theta= 1
PS WS Tol= 0.01
PS Volume Tol= 0.01
PS Max Iterations= 20
PS Equation= 0
PS Advance Time Step=-1
PS Target Courant=0.9
PS Time Slices= 1
PS Iterate With 2D=0
PS Project Initial WSE from DS=-1
PS Ramp Up Initial WSE from US=-1
PS Cores=0
UNET D1D2 MaxIter= 0
UNET D1D2 ZTol=0.01
UNET D1D2 QTol=0.1
UNET D1D2 MinQTol=1
Write IC File= 0
Write IC File at Fixed DateTime=0
Write IC File at Sim End=0
Echo Input=False
Echo Parameters=False
Echo Output=False
Write Detailed= 0
HDF Write Warmup=0
HDF Write Time Slices=0
HDF Flush=0
HDF Compression= 1
HDF Chunk Size= 1
HDF Spatial Parts= 1
HDF Use Max Rows=0
HDF Fixed Rows= 1
Calibration Method= 0
Calibration Iterations= 20
Calibration Max Change=0.05
Calibration Tolerance=0.2
Calibration Maximum=1.5
Calibration Minimum=0.5
Calibration Optimization Method= 1
WQ AD Non Conservative
WQ ULTIMATE=-1
WQ Max Comp Step=1HOUR
WQ Output Interval=15MIN
WQ Output Selected Increments= 0
WQ Create Restart=0
WQ Fixed Restart=0
WQ System Summary=0
WQ Write To DSS=0
Sorting and Armoring Iterations= 10
XS Update Threshold= 0.02
Bed Roughness Predictor= 0
Processes Affected by Predictor=Sediment Only
Hydraulics Update Threshold= 0.02
Energy Slope Method= 1
Volume Change Method= 1
Sediment Retention Method= 0
Sediment TS Multiplier= 1
Warm Up Method= 0
XS Weighting Method= 0
Number of US Weighted Cross Sections= 1
Number of DS Weighted Cross Sections= 1
Upstream XS Weight=0
Main XS Weight=1
Downstream XS Weight=0
Number of DS XS's Weighted with US Boundary= 1
Upstream Boundary Weight= 1
Weight of XSs Associated with US Boundary= 0
Number of US XS's Weighted with DS Boundary= 1
Downstream Boundary Weight= 0.5
Weight of XSs Associated with DS Boundary= 0.5
Percentile Method= 0
Sediment Output Level= 3
Mass or Volume Output= 0
Output Increment Type= 1
Profile and TS Output Increment= 1
Transport Output Increment 1
XS Output Flag= 0
XS Output Increment= 10
Read HDF5 Sediment Hotstart= 0
Sediment Hotstart Type= 0
Write Gradation File= 0
Read Gradation Hotstart= 0
Write HDF5 File= 1
Write Binary Output= 1
Write DSS Sediment File= 0
DSS Sediment Output Type= 1
SV Curve= 0
Specific Gage Flag= 0
Subcell Erosion Methods= 0
Subcell Deposition Methods= 0
Advection Scheme= 1
Matrix Solver= 0
Implicit Weighting Factor= 1
Maximum Outer Loop Convergence Iterations= 5
Convergence Maximum Absolute= 0.001
Convergence RMSE= 0.0001
Grain Fractions Max Abs Error= 0.001
Max Subgrid Regions= 1
Max Subgrid Length Scale= 3.402823E+38
Initial Layer Thickness= 3
Min Layer Thickness= 0.1
Max Layer Thickness= 6
Number of Layers= 5

--- LtleTrbbCk.f01 (steady flow) ---

Flow Title=Flow
Program Version=6.60
Number of Profiles= 1
Profile Names=P100yr
River Rch & RM=LtleTrbbCk,Main,8913
     822
River Rch & RM=LtleTrbbCk,Main,5984
     972
River Rch & RM=LtleTrbbCk,Main,4195
    1110
Boundary for River Rch & Prof#=LtleTrbbCk,Main            , 1
Up Type= 0
Dn Type= 3
Dn Slope=0.028552
DSS Import GetInterval= 0
DSS Import GetPeak= 0
DSS Import FillOption= 0

--- LtleTrbbCk.g01 (geometry) ---

Geom Title=Geometry
Program Version=6.60

River Reach=LtleTrbbCk      ,Main
Reach XY= 30
1615823.58714399488076.463753594     1615646.067      487922.885
     1615588.893      487562.252     1615294.962      487344.552
     1615084.684      487022.8581614784.80538953486748.530662106
      1614695.28      486491.437     1614729.639      486320.786
     1614690.681      485753.833     1614447.894      485495.021
1614278.25135283485448.106679968      1613691.56      484947.371
     1613661.354      484871.668     1613724.777      484709.413
     1613631.198      484504.194     1613599.073      484246.593
     1613444.471      484178.627     1613314.311      483827.048
       1613114.3      483682.506     1613102.572      483508.786
       1612825.5       483529.31     1612809.374      483396.638
      1612580.68      483049.198     1612380.832      482998.613
     1612289.566      482871.555     1611904.341      482618.937
     1611786.013        482611.2     1611517.361       482468.75
     1611231.111      482073.333     1610813.333      481861.111

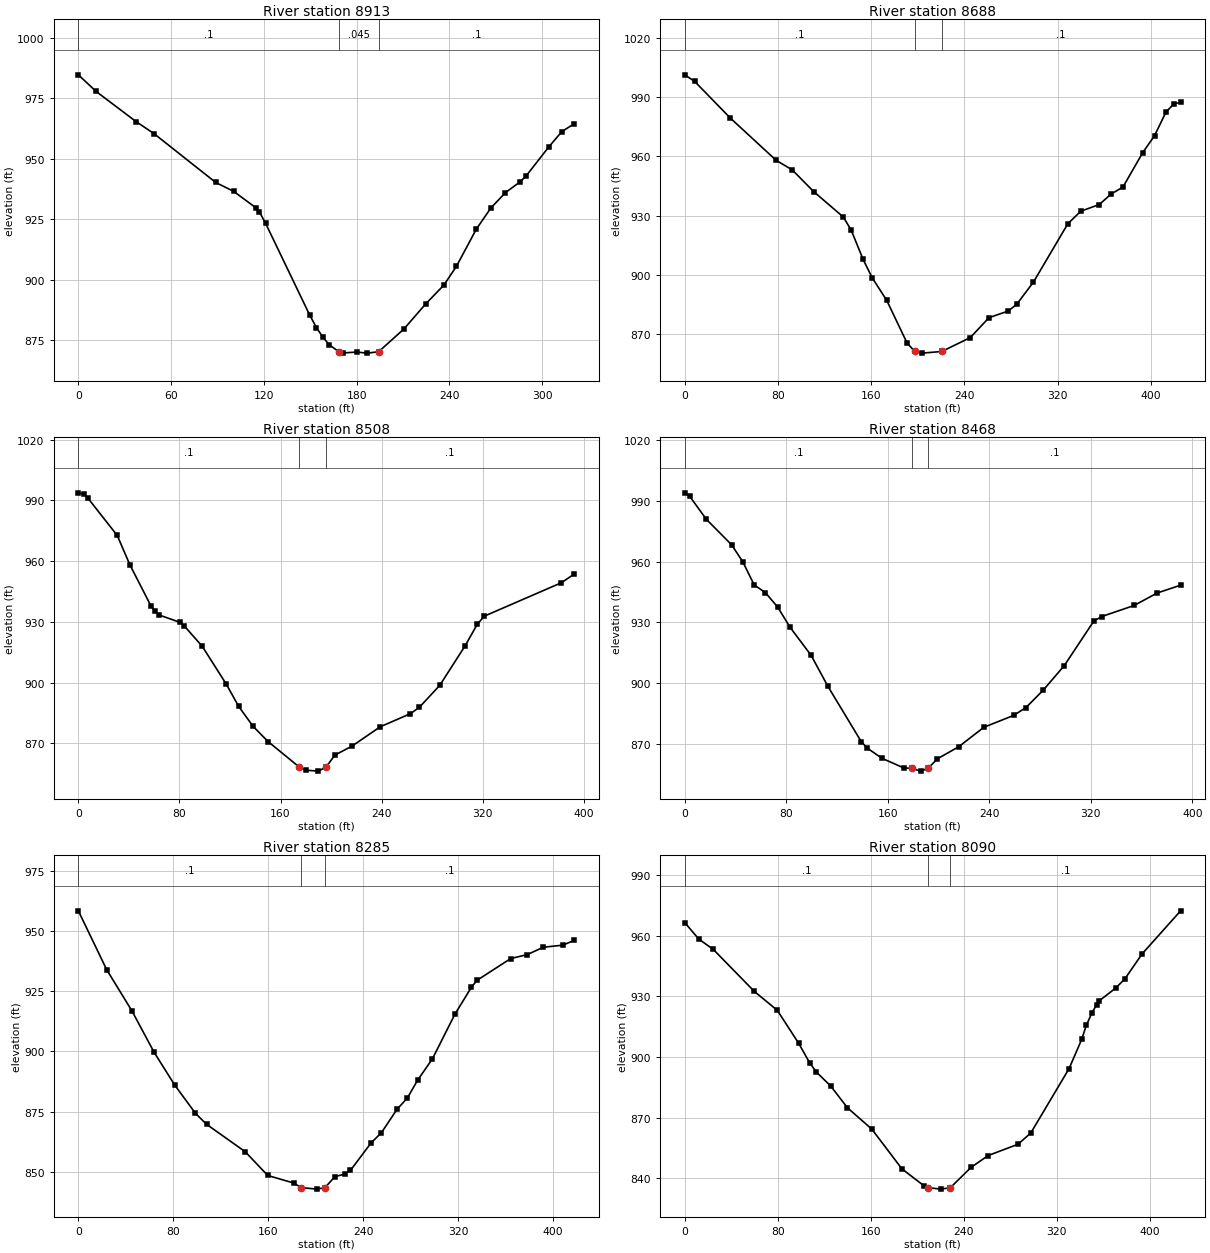
Type RM Length L Ch R = 1 ,8913    ,216,225.3,232.5
XS GIS Cut Line= 2
1615877.20806803487892.7461613931615683.82112887488148.544340008
#Sta/Elev= 30
       0   984.6    11.5  977.74    37.3  965.31      49  960.29    88.8  940.18
   100.5  936.47   114.6   929.8     117  928.14   121.1  923.29   149.7   885.3
     154  880.23   158.1  876.33   162.2  873.21   168.4  870.32   171.3  869.79
   180.1  870.15   186.9  869.71   194.2  870.29   210.6  879.71   224.6  890.01
   236.4  897.82   244.5  905.54   257.4  920.93   266.8  929.65   276.2  935.96
   285.6   940.4   289.7  942.95   304.3   954.9   312.7  961.19320.6731  964.39
#Mann= 3 ,-1,0
       0      .1       0   168.4    .045       0   194.2      .1       0
Bank Sta=168.4,194.2
XS Rating Curve= 0 ,0
Exp/Cntr(USF)=0,0
Exp/Cntr=0.3,0.1

Type RM Length L Ch R = 1 ,8688    ,178,179.9,180.4
XS GIS Cut Line= 6
1615834.39648008487809.2953484211615751.73030683487839.534789249
1615678.90794593487857.4766824991615581.81135534487881.398550674
1615508.98899442487899.3404439241615424.02951868487920.272488669
#Sta/Elev= 30
       0 1001.38     8.5  998.05    39.1  979.47    78.4  958.06    92.2  953.22
   110.7  942.16   136.1   929.3   142.9  922.58     153  907.87   160.9  898.47
   173.3  887.08   190.7  865.54   197.3861.1588   203.7  860.32  220.62861.1573
     245   868.2   261.1  878.29   277.5  881.65   284.8  885.02   299.2  896.31
   328.7  925.87   339.8  932.24   355.7  935.64   365.9  940.98     376  944.47
   392.9  961.86   403.1  970.53     413  982.58   419.9  986.76   425.5  987.39
#Mann= 3 ,-1,0
       0      .1       0   197.3    .045       0  220.62      .1       0
Bank Sta=197.3,220.62
XS Rating Curve= 0 ,0
Exp/Cntr(USF)=0,0
Exp/Cntr=0.3,0.1

Type RM Length L Ch R = 1 ,8508    ,40.2,39.5,39.2
XS GIS Cut Line= 2
1615791.29884388487666.0438319181615402.89518065487721.680032327
#Sta/Elev= 30
       0  993.76     4.3  993.09     7.6  991.12    30.8  972.67    40.7   958.3
    57.3  938.04    60.6  935.24    63.9  933.38    80.5  929.71    83.8  927.98
    98.1  917.85     117  899.25   126.9  888.17   138.3  878.32   150.1  870.83
  174.75858.2455   179.9  856.67   189.9  856.19  196.09858.2427   203.1  864.17
   216.4  868.49   238.9  878.11   262.8  884.59   269.9  887.76     286  898.59
   305.9  917.97   315.8   928.9   321.3  932.81   382.1  949.27   392.4  953.59
#Mann= 3 ,-1,0
       0      .1       0  174.75    .045       0  196.09      .1       0
Bank Sta=174.75,196.09
XS Rating Curve= 0 ,0
Exp/Cntr(USF)=0,0
Exp/Cntr=0.3,0.1

Type RM Length L Ch R = 1 ,8468    ,189.3,182.5,177.8
XS GIS Cut Line= 3
1615784.38297509 487630.993005351615638.16836536 487647.07942702
1615398.15098245487688.864546222
#Sta/Elev= 30
       0  994.06     3.9  992.33    17.1  980.94    36.9   968.4    45.8  959.91
    54.7  948.55    63.6  944.71    73.2   937.6    83.1  927.52    99.6  913.72
   112.8  898.42   139.2  870.98   143.9  867.86   155.4  862.87   172.5  858.13
   179.1  857.92   185.8  856.53  191.71  857.89   199.1  862.64   215.8  868.54
   235.7  878.21   259.1  884.05   268.9  887.97   282.4  896.51     299  908.65
   322.3  930.67   328.4  932.89     354  938.38   372.3  944.57   390.7  948.42
#Mann= 3 ,-1,0
       0      .1       0   179.1    .045       0  191.71      .1       0
Bank Sta=179.1,191.71
XS Rating Curve= 0 ,0
Exp/Cntr(USF)=0,0
Exp/Cntr=0.3,0.1

Type RM Length L Ch R = 1 ,8285    ,197.6,195.4,193
XS GIS Cut Line= 2
1615658.44570668487347.4359417781615383.64077226487662.187458142
#Sta/Elev= 30
       0  958.34    23.9   933.9    45.2  916.77    63.9  899.57    81.2  886.01
    98.7  874.28     108  869.74   140.6  858.35   159.6  848.48   181.4  845.36
   187.8843.4587     201  842.82  207.84 843.458   216.2  848.02   224.3  849.03
   229.3  850.62   246.7  862.03   255.4  866.26   268.5  875.96   277.2  880.63
   285.9  888.06   298.3  896.88   317.3  915.45   331.2  926.63   335.9   929.5
   364.3  938.53   378.1  940.14   391.7  943.22     408  944.08   417.8  946.04
#Mann= 3 ,-1,0
       0      .1       0   187.8    .045       0  207.84      .1       0
Bank Sta=187.8,207.84
XS Rating Curve= 0 ,0
Exp/Cntr(USF)=0,0
Exp/Cntr=0.3,0.1

Type RM Length L Ch R = 1 ,8090    ,300.2,301.3,308
XS GIS Cut Line= 6
1615478.92737475487205.3726717531615425.21422759487275.584145501
1615390.29763076487341.9531072531615343.64122801487430.438166499
1615310.23381451487497.8015488391615269.31198034487575.647849843
#Sta/Elev= 30
       0  966.44    12.2  958.24    24.6  953.17    59.8  932.47    79.6   923.1
    97.9  906.91   107.5  897.11   113.3  892.56   125.5  885.72     140  874.91
   160.9   864.4   186.8  844.76   205.6  836.45  209.61835.4262   220.2  834.72
  228.49 835.425   246.2  845.41     261  851.31   286.7   856.9   297.7  862.46
   330.6  894.25   341.6  908.85   345.4  915.59   350.3  921.82   354.4  925.95
   356.8  927.88   371.1  934.25   378.7  938.67   393.5     951   426.6  972.26
#Mann= 3 ,-1,0
       0      .1       0  209.61    .045       0  228.49      .1       0
Bank Sta=209.61,228.49
XS Rating Curve= 0 ,0
Exp/Cntr(USF)=0,0
Exp/Cntr=0.3,0.1

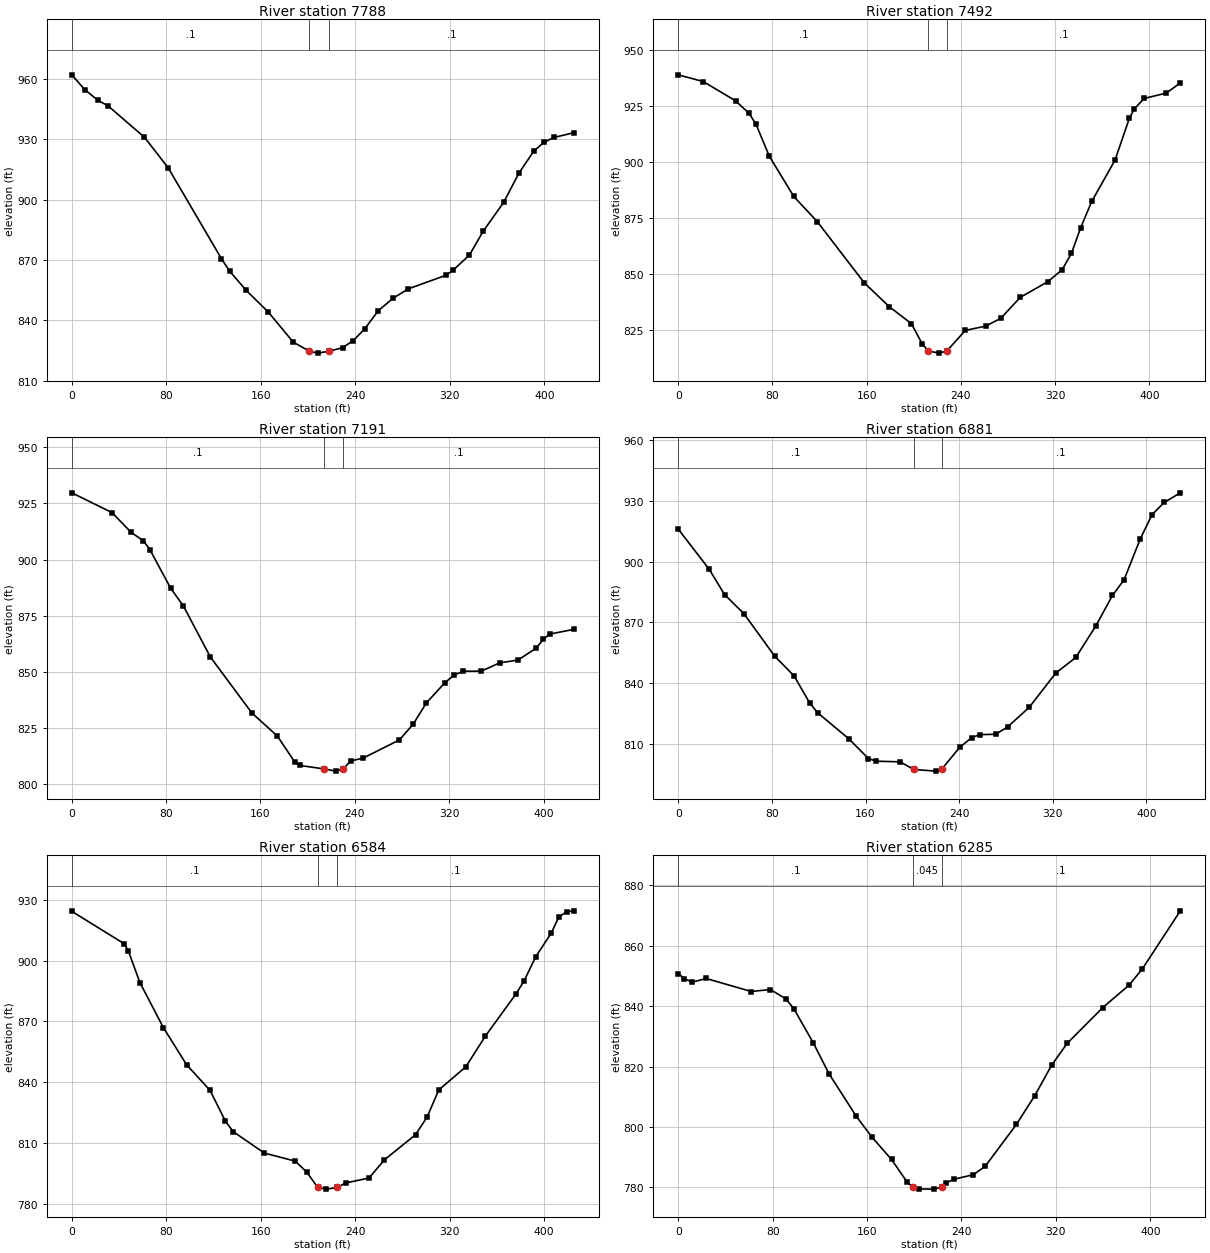
Type RM Length L Ch R = 1 ,7788    ,298.8,296.9,294.5
XS GIS Cut Line= 6
1615354.76686193487021.0708750041615287.04947767487076.483821929
1615229.00628668487123.9811022581615151.61503726 487187.31037192
1615093.57151817487234.8073241711615025.85446201487290.220599175
#Sta/Elev= 30
       0   961.9      11  954.56    22.2  949.22    30.7   946.5    61.5  930.93
    81.6  915.77   126.7  870.65   133.7  864.43   147.7  854.92   166.4  844.15
   187.5  829.23  201.16824.7429   208.3   823.8  217.88824.7437   229.3  826.53
   238.4  830.06     248  835.86   259.6  844.95   272.3  851.17     285  855.72
   316.7  862.43   322.6  864.84   336.6  872.47   348.2  884.23   365.6  898.63
   378.5  913.12     391  923.96   399.5  928.34     408  930.81     425  933.16
#Mann= 3 ,-1,0
       0      .1       0  201.16    .045       0  217.88      .1       0
Bank Sta=201.16,217.88
XS Rating Curve= 0 ,0
Exp/Cntr(USF)=0,0
Exp/Cntr=0.3,0.1

Type RM Length L Ch R = 1 ,7492    ,298.9,300.2,305
XS GIS Cut Line= 6
1615122.62690626486750.8220716711615072.59518218 486822.60670501
 1615029.7107535486884.1367656741614972.53107785486966.176627845
1614929.73391934487027.7670558391614876.33277942487098.596310511
#Sta/Elev= 30
       0  938.78    21.2   935.8    48.7   927.2    60.1  921.65      66  916.81
    77.3  902.57      98  884.68     118  873.46   157.8  846.29     179  835.65
   197.9  828.05   207.3  818.88  212.43815.9014   221.5  814.92  228.06815.9004
   243.7  825.04     261  826.94   273.9  830.45   290.3  839.73   313.9  846.77
   325.9  852.06   333.8  859.31   341.6  870.73     351  882.43   370.7  900.74
     383  919.52   387.2  923.66   395.5  928.25   414.3  930.67   426.2  935.18
#Mann= 3 ,-1,0
       0      .1       0  212.43    .045       0  228.06      .1       0
Bank Sta=212.43,228.06
XS Rating Curve= 0 ,0
Exp/Cntr(USF)=0,0
Exp/Cntr=0.3,0.1

Type RM Length L Ch R = 1 ,7191    ,300,309.9,317.2
XS GIS Cut Line= 6
  1614968.606545486625.9952215851614891.17986259486667.598484844
1614824.99331518486703.5268906651614739.68508685486755.842074752
1614675.97688092486795.4131898431614601.67059909486841.565984666
#Sta/Elev= 30
       0  929.74    34.1  920.95    50.4   912.1    60.8  908.35    66.2  904.48
    83.9  887.22    94.7  879.33   117.5  856.65   152.7  831.74   174.4  821.41
   189.2  809.78   193.1  808.39  214.06806.8147   223.9  805.84  230.27806.8148
   236.4  810.36     247  811.62   277.8  819.74   289.4  826.67   300.7  836.24
   316.4  845.23   324.1  848.58   331.9  850.31   347.3  850.35   362.8  854.05
   378.2  855.26   393.7  860.56   399.9   864.6   405.2  866.85   425.7  868.95
#Mann= 3 ,-1,0
       0      .1       0  214.06    .045       0  230.27      .1       0
Bank Sta=214.06,230.27
XS Rating Curve= 0 ,0
Exp/Cntr(USF)=0,0
Exp/Cntr=0.3,0.1

Type RM Length L Ch R = 1 ,6881    ,301.2,297.2,294.2
XS GIS Cut Line= 6
1614911.21623984486475.8915191741614821.08190568486468.564434096
1614746.51545376 486454.822663681614649.72266833486428.815169752
1614577.95739192486407.0452001691614494.25283493486381.654502928
#Sta/Elev= 30
       0  916.03    26.5  896.14    39.6  883.69    56.1  874.29    82.4  853.32
      99  843.56   112.3  830.23     119  825.45   145.7  812.55   162.4  802.83
   169.1   801.5   189.5  801.18  201.34797.4045   220.1   796.6   224.9 797.404
   240.4  808.32   250.6  813.07   257.4  814.61   271.1  814.78   281.4   818.4
   299.9  828.14   322.5  844.97   339.6  852.67   356.8  868.32   370.9  883.26
   380.8  890.94   394.8  911.34   404.8  923.16   415.1  929.14   428.9  933.91
#Mann= 3 ,-1,0
       0      .1       0  201.34    .045       0   224.9      .1       0
Bank Sta=201.34,224.9
XS Rating Curve= 0 ,0
Exp/Cntr(USF)=0,0
Exp/Cntr=0.3,0.1

Type RM Length L Ch R = 1 ,6584    ,301.4,299.5,298.5
XS GIS Cut Line= 6
1614919.42390059486135.2058488431614832.11928518486143.136935338
1614757.26740076486149.2638915931614657.34109142486153.253056839
1614582.37372167486155.4577768451614494.91129817486158.030278251
#Sta/Elev= 30
       0   924.3    44.6  908.24    47.9  904.76    57.8  889.07    77.6  866.95
    97.3  848.61   117.1  836.02   130.2  820.78   136.8  815.62   163.2  805.07
   189.4  801.09   199.3  795.53  208.35788.1077   215.7   787.3  224.63 788.106
   232.1  790.34   251.8  792.79   264.9  801.78   291.2  814.15     301  822.85
   310.9  836.21   333.9  847.69   350.3  862.72   376.5  883.74   383.1  889.94
   392.9  901.77   406.1  913.52   412.6  921.52   419.2  924.07   425.3  924.54
#Mann= 3 ,-1,0
       0      .1       0  208.35    .045       0  224.63      .1       0
Bank Sta=208.35,224.63
XS Rating Curve= 0 ,0
Exp/Cntr(USF)=0,0
Exp/Cntr=0.3,0.1

Type RM Length L Ch R = 1 ,6285    ,308.7,301.1,293.3
XS GIS Cut Line= 6
1614916.37731875485825.6752999281614829.59665242485836.872455999
1614755.21327101485846.4702058431614656.03564784485859.266768172
1614581.65226643485868.8645180021614495.89981325485888.032130584
#Sta/Elev= 30
       0   850.8     5.3  849.09      12  847.97    23.7  849.17    61.8  844.86
    78.1  845.51    91.3  842.39      98  839.12   114.5  827.79   127.7  817.63
   150.9  803.49   164.1  796.62   180.7  789.21   193.9  781.75  198.54780.0576
   203.8  779.42     217  779.38  223.18780.0588     227  781.41   233.6  782.68
   250.1  784.15   260.1  786.95   286.5  800.81   302.1  810.37   316.3  820.39
   329.5  827.67   359.7  839.53     382  846.98   393.3  852.39   425.4  871.59
#Mann= 3 ,-1,0
       0      .1       0  198.54    .045       0  223.18      .1       0
Bank Sta=198.54,223.18
XS Rating Curve= 0 ,0
Exp/Cntr(USF)=0,0
Exp/Cntr=0.3,0.1

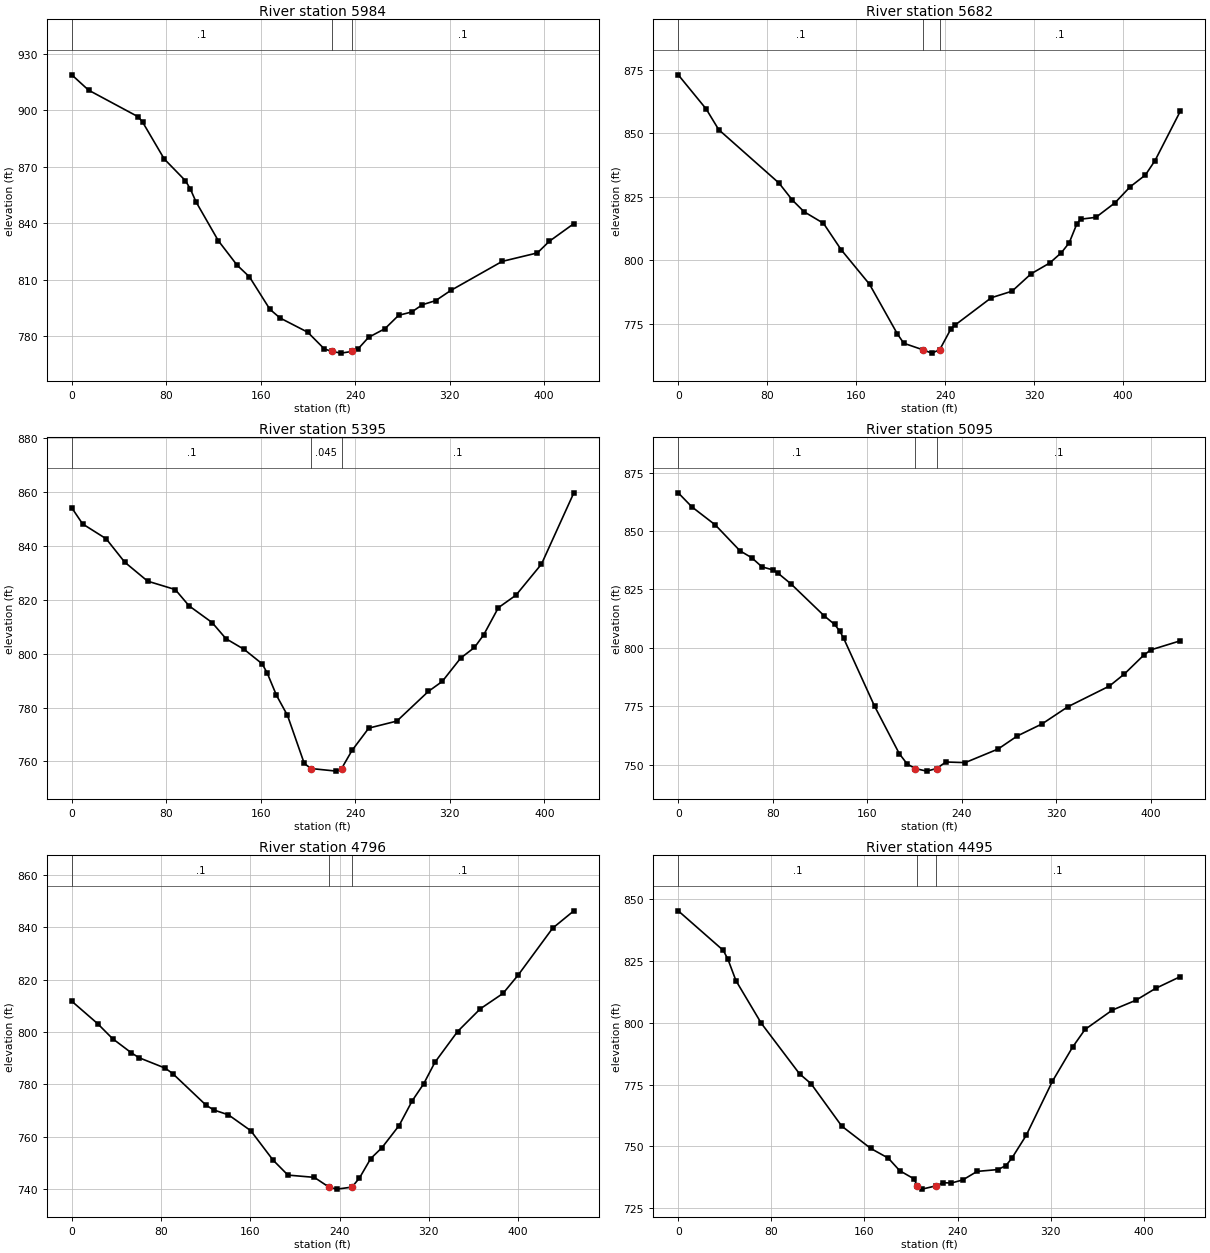
Type RM Length L Ch R = 1 ,5984    ,304.2,301.4,296.3
XS GIS Cut Line= 6
1614698.95288484485473.0080262571614635.33916692 485533.08763051
1614580.81302926485584.5845747591614509.38600676485654.595917672
1614457.76012576 485709.163393841614397.85965501485773.174748749
#Sta/Elev= 30
       0  918.81    14.2  910.69    56.5  896.45    60.2   893.5    78.3  874.15
    96.3  862.57   100.3  858.37   105.3  851.31   124.1  830.76     140  817.78
   150.5  811.54   167.8  794.33   176.4  789.71   199.9  782.13   213.9  773.29
  220.13771.9805   228.2  771.04  237.71771.9797   242.1  772.98   251.4  779.42
   265.3  784.02   276.9  791.13     288  792.89     297  796.75   308.2   798.9
     321   804.3   364.6  819.75   394.4  824.25   404.5  830.41   425.3   839.8
#Mann= 3 ,-1,0
       0      .1       0  220.13    .045       0  237.71      .1       0
Bank Sta=220.13,237.71
XS Rating Curve= 0 ,0
Exp/Cntr(USF)=0,0
Exp/Cntr=0.3,0.1

Type RM Length L Ch R = 1 ,5682    ,285.1,287.1,286.9
XS GIS Cut Line= 6
1614422.05153576485267.370314166 1614373.9171176485352.669684261
1614331.38833126485428.1268824191614300.45991543 485527.95214209
 1614278.6886335 485599.722011671614253.29760817485683.428537175
#Sta/Elev= 30
       0  873.06    25.1  859.61    36.4  851.45    90.6   830.4   102.6   823.7
   113.1  819.11   130.6  814.54   146.5  804.13     172  790.53   197.1  770.92
   202.8  767.27  219.88764.7002     228  763.37  235.12764.7021   245.2  772.91
   248.7  774.35   281.5   785.2   300.2  787.79   317.3  794.63   334.1   798.9
   344.6  802.98   351.6  806.87   358.4  814.25   361.9  816.16   375.6  816.89
   392.7   822.6   406.4  828.93   420.1  833.57   428.8  839.29   451.5  858.73
#Mann= 3 ,-1,0
       0      .1       0  219.88    .045       0  235.12      .1       0
Bank Sta=219.88,235.12
XS Rating Curve= 0 ,0
Exp/Cntr(USF)=0,0
Exp/Cntr=0.3,0.1

Type RM Length L Ch R = 1 ,5395    ,298,300,301.8
XS GIS Cut Line= 6
1614223.43218234485110.4903785881614176.21147625485184.154929429
1614135.73681967 485247.295879261614081.77039218485331.484031096
 1614041.2954075485394.6249809271613994.07470143485468.289531752
#Sta/Elev= 30
       0  854.17     9.2  848.18    29.1  842.68    44.8     834    64.2  826.94
    87.6  823.82    99.3  817.76   118.8  811.56   130.5  805.58     146  801.57
   161.2  796.23   165.5  792.75   173.3  784.53   182.6  777.08   196.8  759.24
  202.53757.3514     224  756.39   228.4757.3533   237.2  764.06   251.4  772.36
   275.2  774.98   301.9  786.01   313.6  789.69   329.2  798.37   340.9  802.32
   348.7  807.02   361.1  817.08     376  821.73   397.6  833.27     425  859.74
#Mann= 3 ,-1,0
       0      .1       0  202.53    .045       0   228.4      .1       0
Bank Sta=202.53,228.4
XS Rating Curve= 0 ,0
Exp/Cntr(USF)=0,0
Exp/Cntr=0.3,0.1

Type RM Length L Ch R = 1 ,5095    ,294.7,299.2,307.1
XS GIS Cut Line= 6
 1614013.2367366484950.7111705841613955.13449059485016.135908499
1613905.33242483485072.2138803451613838.92967051485146.984728172
1613789.12760475485203.0627000031613731.02535875485268.487437919
#Sta/Elev= 30
       0  866.34    11.5  860.35    31.4  852.59    52.3  841.52    62.2  838.57
    70.9  834.66    79.8  833.42    84.2  832.06    95.5  827.35   123.6  813.69
   132.4  810.02   136.8  807.11     140  804.13   166.2  775.04   187.1  754.76
   193.8  750.32  200.72748.3702   210.3  747.27  218.65748.3712   226.6  751.18
   242.9  750.91   270.8  756.74     287  762.31     308  767.48   329.9  774.84
     365  783.68   377.7  788.85   393.9  796.82   400.1  799.15     425  803.03
#Mann= 3 ,-1,0
       0      .1       0  200.72    .045       0  218.65      .1       0
Bank Sta=200.72,218.65
XS Rating Curve= 0 ,0
Exp/Cntr(USF)=0,0
Exp/Cntr=0.3,0.1

Type RM Length L Ch R = 1 ,4796    ,301.4,300.8,299.5
XS GIS Cut Line= 6
 1613900.1263985484848.7865056691613798.98782125484871.767758921
1613716.63398334484885.4888600861613619.22374509484908.765716419
 1613546.5562395 484927.324734421613461.77753767484948.976922095
#Sta/Elev= 30
       0  811.78    23.1  803.24    36.5   797.5    53.4  792.07    60.1  790.23
    83.6  786.24    90.4  784.16   120.4  772.04   127.3  770.23   140.4  768.38
   160.4  762.32   180.3  751.12   193.7  745.36   217.3   744.5  230.46 740.775
   237.6     740  251.06740.7733   257.8  744.25   267.9  751.68     278  755.86
   293.3  764.28   305.1  773.76   315.3   780.2   325.4  788.44   345.7   800.2
   366.1  808.89   386.4  814.75   399.9  821.71   430.9  839.68   449.9  846.31
#Mann= 3 ,-1,0
       0      .1       0  230.46    .045       0  251.06      .1       0
Bank Sta=230.46,251.06
XS Rating Curve= 0 ,0
Exp/Cntr(USF)=0,0
Exp/Cntr=0.3,0.1

Type RM Length L Ch R = 1 ,4495    ,295.8,300.6,302.4
XS GIS Cut Line= 6
 1613889.5713015484522.4731819181613810.60033084484560.154537007
1613742.91148984484592.4530288431613652.65904567 484635.51724717
1613583.97348751484666.1320153331613492.66494308484687.382957086
#Sta/Elev= 30
       0   845.4    38.7  829.39    42.7  825.79    49.6  817.12    71.4  799.85
   104.2  779.42   114.1  775.42   140.5  758.24   165.4  749.21   180.5  745.27
   190.3  740.19   202.3  736.96  205.54734.0715   209.5  732.73  221.63734.0719
   227.7  735.33   234.6   735.2   244.5  736.45   256.8  739.91   274.8  740.65
   281.6  742.29   286.6  745.21     299  754.51   321.5  776.39   338.8  790.19
   349.5  797.36     373  805.22   393.3  809.21   410.1  813.98   431.4  818.76
#Mann= 3 ,-1,0
       0      .1       0  205.54    .045       0  221.63      .1       0
Bank Sta=205.54,221.63
XS Rating Curve= 0 ,0
Exp/Cntr(USF)=0,0
Exp/Cntr=0.3,0.1

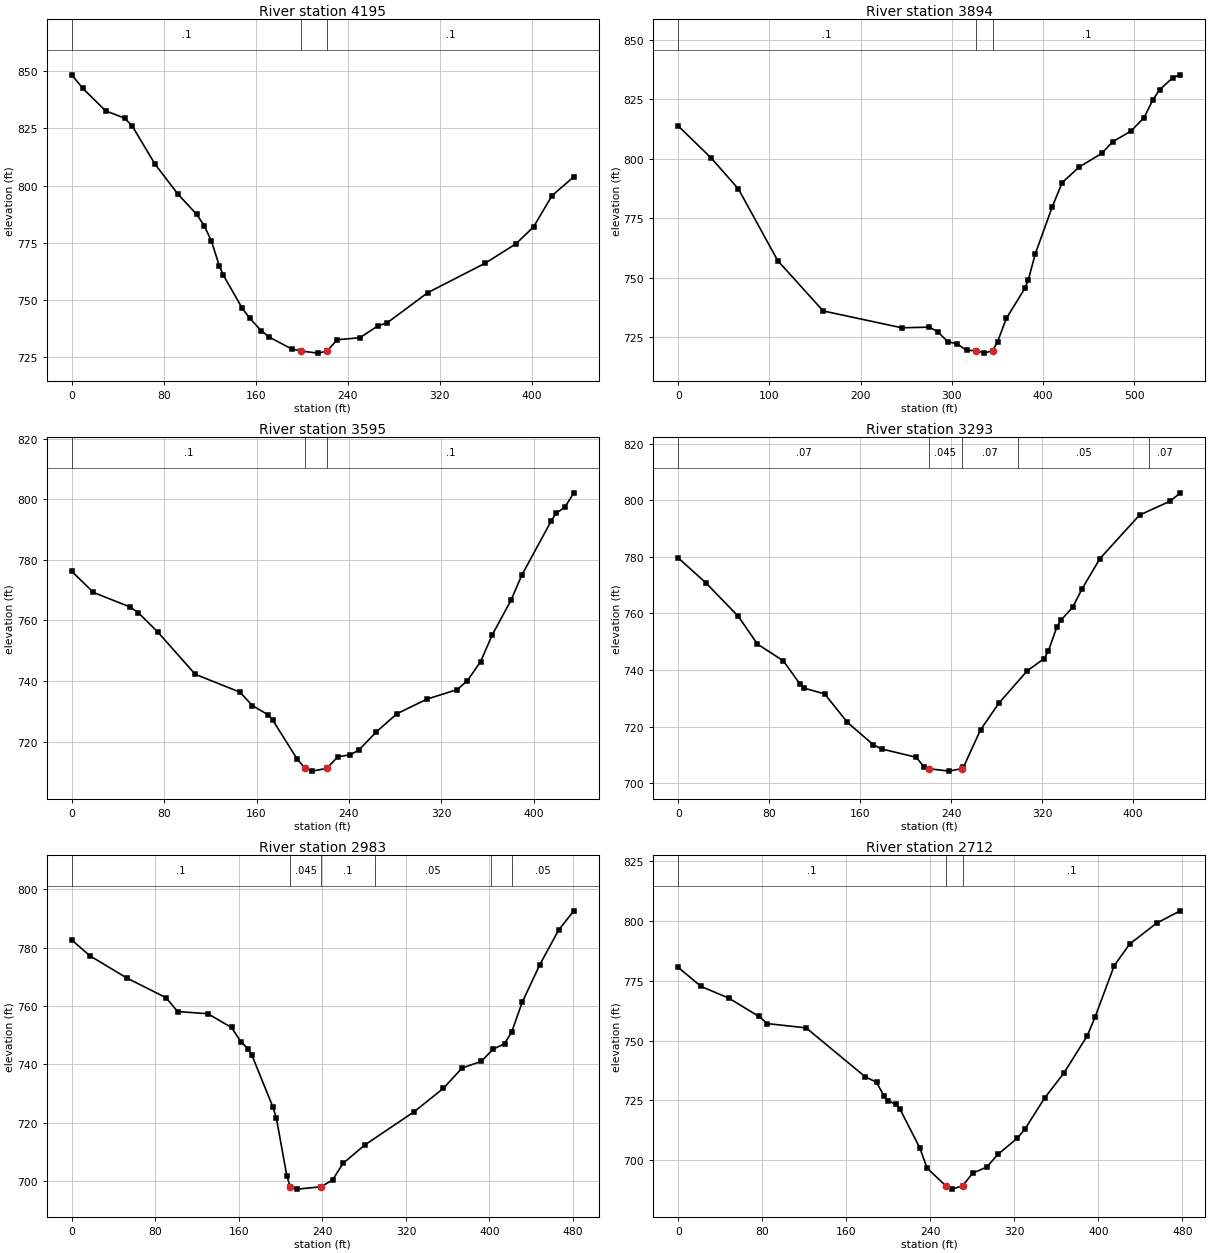
Type RM Length L Ch R = 1 ,4195    ,305.5,301.1,294.9
XS GIS Cut Line= 6
1613828.11145067484311.5418452621613740.90985343484320.581197262
1613666.48611775484330.2822933351613567.00829834 484340.54933317
1613494.03764376484367.5410770921613411.07783592484416.282777503
#Sta/Elev= 30
       0  848.41     9.6   842.5    29.4   832.7    45.9  829.47    52.5  826.12
    72.3  809.46    92.1  796.42   108.6  787.46   115.2  782.52   121.5  775.73
   128.5  764.72   131.8  760.91   148.3  746.39   154.9  742.01   164.8  736.58
   171.5  733.86   191.2  728.64  199.64727.6795   214.3  726.78  222.19727.6778
   230.8  732.62   250.6  733.51   266.5  738.74   274.3     740   309.9  753.26
   359.9  766.14   386.5  774.59   401.7  781.92   417.8  795.61   436.8  803.86
#Mann= 3 ,-1,0
       0      .1       0  199.64    .045       0  222.19      .1       0
Bank Sta=199.64,222.19
XS Rating Curve= 0 ,0
Exp/Cntr(USF)=0,0
Exp/Cntr=0.3,0.1

Type RM Length L Ch R = 1 ,3894    ,296.6,298.4,298.9
XS GIS Cut Line= 5
1613759.10219342 484165.34117124 1613489.3655631484123.557670994
1613388.57886517484179.0795117621613321.76108542484213.144076169
1613243.80684501484252.886122674
#Sta/Elev= 30
       0  813.75    36.1  800.29      66  787.26   109.1   757.1   158.9  735.96
   245.1  728.88   275.3  729.14   284.9  727.13   295.4  723.02   305.4  722.17
   316.3  719.38  326.77 719.286   335.6  718.22  344.65719.2863   350.1  722.97
   359.8  732.87   380.3  745.62   383.8     749   391.5  759.98   409.9  779.55
   420.9   789.9   439.3   796.4   464.4  802.24   476.6  807.21   496.1  811.49
   510.7  817.23   520.5  824.79   527.7  828.95   542.4  834.13   550.5  835.26
#Mann= 3 ,-1,0
       0      .1       0  326.77    .045       0  344.65      .1       0
Bank Sta=326.77,344.65
XS Rating Curve= 0 ,0
Exp/Cntr(USF)=0,0
Exp/Cntr=0.3,0.1

Type RM Length L Ch R = 1 ,3595    ,303.1,301.9,304.6
XS GIS Cut Line= 6
1613534.02017534483795.879490763  1613452.739498 483828.27903226
1613382.99751151483855.8662474161613290.00819618483892.649638429
1613229.95319818483941.7374667531613157.23910476484002.501780927
#Sta/Elev= 30
       0  776.19    18.8  769.23    50.4  764.45    57.5   762.6    74.4  756.21
   106.9  742.23   145.7  736.31   156.3  731.91   170.3   728.8   173.9   727.2
   195.1   714.3     202711.1771   208.3  710.26  220.83711.1762   230.4  714.99
   241.2  715.66   248.8  717.26   263.8  723.23   281.6  729.21   307.5  734.01
   333.8  737.17   342.6  740.12     354  746.37   364.2  755.28   380.4  766.68
   389.6  774.83   415.3   792.9   419.5  795.35     427  797.36   434.8  802.11
#Mann= 3 ,-1,0
       0      .1       0     202    .045       0  220.83      .1       0
Bank Sta=202,220.83
XS Rating Curve= 0 ,0
Exp/Cntr(USF)=0,0
Exp/Cntr=0.3,0.1

Type RM Length L Ch R = 1 ,3293    ,319.8,310,281.1
XS GIS Cut Line= 6
1613321.25518093483584.5380499211613233.92891201483634.992345333
1613162.24729684483666.2091464251613075.61525226483716.297628924
1613009.33159217483751.3897503321612935.07386668483797.930995837
#Sta/Elev= 30
       0  779.63    24.3  770.82    52.9  758.94    69.7  749.15    92.5  743.22
   107.3   734.9   110.9  733.56   128.8  731.54   148.9  721.44   171.7  713.53
     179  712.06   209.2  709.15   216.6  705.62  220.19705.1032   238.2  704.23
  249.35 705.105   250.9  705.61     266  718.87   282.1  728.28   307.1  739.74
     322  744.05   325.7  746.82   333.1  755.21   336.8  757.67     347   762.2
   355.4  768.78     371  779.39   405.8  794.78   432.9  799.73   441.7  802.65
#Mann= 5 ,-1,0
       0     .07       0  220.19    .045       0  249.35     .07       0
  299.11     .05       0  414.11     .07       0
Bank Sta=220.19,249.35
XS Rating Curve= 0 ,0
Exp/Cntr(USF)=0,0
Exp/Cntr=0.3,0.1

Type RM Length L Ch R = 1 ,2983    ,261,271.7,293
XS GIS Cut Line= 5
1613041.33658363483301.1949088561612980.15907834483456.504841417
1613002.46743268483557.1027373371612961.89992851483649.754454926
1612911.35803483483747.113512173
#Sta/Elev= 30
       0  782.63    17.5  777.19    52.7  769.61    90.4  762.82   101.3   758.1
   130.3  757.34     153  752.62     162  747.69     169  745.23   172.4  743.18
   192.5  725.44   195.9   721.6     206  701.59  209.24 697.945   216.1  697.15
  238.67697.9461   249.7  700.28   259.7  705.96   280.4  712.25   327.8  723.69
   355.8  731.72   373.8  738.72   392.2  741.01   403.3  745.14   414.4  747.05
   421.2  751.01   431.3  761.24     448  774.04   466.2  786.04   480.8  792.66
#Mann= 6 ,-1,0
       0      .1       0  209.24    .045       0  238.67      .1       0
  289.97     .05       0  401.11      .1       0  421.11     .05       0
Bank Sta=209.24,238.67
XS Rating Curve= 0 ,0
Exp/Cntr(USF)=0,0
Exp/Cntr=0.3,0.1

Type RM Length L Ch R = 1 ,2712    ,145.4,145.9,142
XS GIS Cut Line= 5
1613013.24817145483288.9207844321612933.11561488483395.832135842
1612868.75019534483427.2484227631612780.85748059 483443.79496268
1612617.55093435483527.340936106
#Sta/Elev= 30
       0  780.65    21.6   772.7      48  767.81    76.7  760.15    84.9  757.11
   121.8  755.32   177.8  734.93   188.8  732.53   196.1  726.72   199.7  724.83
   206.9  723.41   210.9  721.54   230.2  704.92   236.9  696.62   254.8689.1979
   260.3  687.81  270.89689.1974   280.3  694.49   293.7  697.03   304.6  702.44
     323  709.18   330.4  713.12   348.8   725.9   367.3  736.44   389.4  751.93
   396.8   759.7   415.2  781.41   429.9  790.43   455.7  799.22   478.1  804.33
#Mann= 3 ,-1,0
       0      .1       0   254.8    .045       0  270.89      .1       0
Bank Sta=254.8,270.89
XS Rating Curve= 0 ,0
Exp/Cntr(USF)=0,0
Exp/Cntr=0.3,0.1

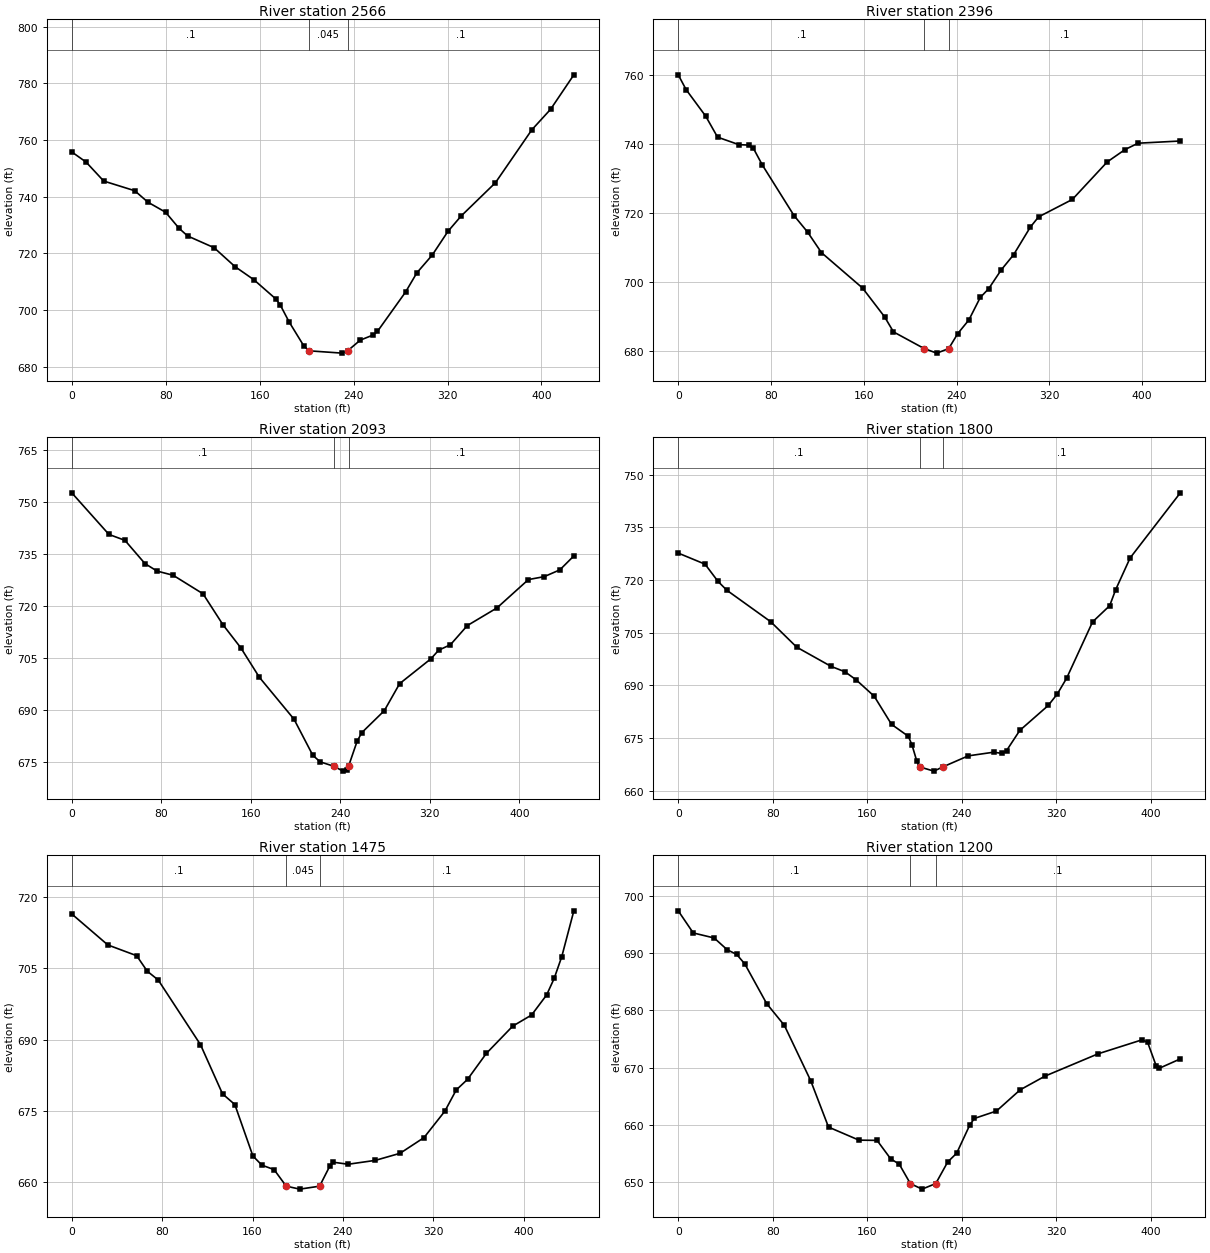
Type RM Length L Ch R = 1 ,2566    ,168.1,169.7,168.3
XS GIS Cut Line= 2
1612930.28131788 483213.492362051612557.09887929483422.285574527
#Sta/Elev= 30
       0   755.8    12.2  752.21    27.2  745.52    53.6  742.11    64.9  738.05
    79.9  734.52    91.4  728.83    98.7  726.13   121.2     722     139  715.33
   155.1  710.69   173.9  703.87   177.6  701.75   185.1  695.81   197.5  687.42
  202.06685.6034   230.2  684.79  234.92685.6043   245.7  689.37   256.6  691.18
   260.3  692.43   284.3  706.36   293.9  713.13     307   719.4   320.4  727.77
   331.7  733.22   360.8  744.92   391.9  763.65   407.8  770.85   427.6  783.01
#Mann= 3 ,-1,0
       0      .1       0  202.06    .045       0  234.92      .1       0
Bank Sta=202.06,234.92
XS Rating Curve= 0 ,0
Exp/Cntr(USF)=0,0
Exp/Cntr=0.3,0.1

Type RM Length L Ch R = 1 ,2396    ,307.1,302.6,292
XS GIS Cut Line= 6
1612849.98807885 483057.701177091612775.66342434483103.865782917
1612713.26000585483145.468718082 1612625.5643151483194.202872589
1612555.14450842483225.240540177  1612474.954052483272.538345844
#Sta/Elev= 30
       0  760.03     6.8  755.73    23.7  748.02    33.9  741.94    52.3  739.76
    60.9  739.63    64.8   738.7    72.5  733.86    99.8  719.19   111.6  714.35
   123.5  708.41   158.9  698.14   177.9  689.79   185.6   685.4  212.18680.5426
   222.9  679.24  233.17680.5441     241  684.91   250.6  688.87   260.4  695.39
   267.7  697.95   278.5  703.41   289.2  707.82   303.6  715.83   310.7  718.79
   339.8  723.85   369.9  734.75   385.3  738.35   396.5  740.18   432.9  740.82
#Mann= 3 ,-1,0
       0      .1       0  212.18    .045       0  233.17      .1       0
Bank Sta=212.18,233.17
XS Rating Curve= 0 ,0
Exp/Cntr(USF)=0,0
Exp/Cntr=0.3,0.1

Type RM Length L Ch R = 1 ,2093    ,291.8,293.3,291.7
XS GIS Cut Line= 6
1612524.96281026482801.5770174261612485.29097359482891.267782927
1612455.08991851482972.8486565051612433.04107809483071.569587678
1612407.38889842483142.0428719221612377.46441759483224.252681255
#Sta/Elev= 30
       0   752.7    33.2   740.7    47.5  738.99    65.4  732.28    76.2  730.12
    90.6  728.91   117.3  723.56   135.1  714.64   151.1  707.96   167.7  699.45
   198.6  687.38   215.4  676.97     222  675.06  234.53673.7705   242.3  672.39
   245.7  672.61  247.32673.7723     255     681   259.2   683.5   279.3  689.83
     293  697.63     321  704.82   327.9  707.29   338.4  708.86   353.5  714.39
     380  719.49   408.1  727.67   422.2  728.51   436.2  730.47   448.7  734.49
#Mann= 3 ,-1,0
       0      .1       0  234.53    .045       0  247.32      .1       0
Bank Sta=234.53,247.32
XS Rating Curve= 0 ,0
Exp/Cntr(USF)=0,0
Exp/Cntr=0.3,0.1

Type RM Length L Ch R = 1 ,1800    ,321,325.3,325.4
XS GIS Cut Line= 6
1612328.24469976 482651.049103261612287.44556876482728.568305179
1612255.00764151482796.1954665041612212.71966834482886.814051673
1612181.00352442482954.7778265031612141.96816942483033.120189503
#Sta/Elev= 30
       0  727.65    22.7   724.5    33.7  719.59    41.2  717.07    78.3  708.13
   100.3   700.9   129.4  695.43   141.2  693.89   150.6  691.61   165.9  686.95
   180.6  678.94   194.8  675.55   197.9   673.1     202  668.48  204.48666.8307
   216.5  665.64  223.97666.8298   245.5  669.98     267  671.02   274.5  670.67
     278  671.49   289.2  677.22   313.3  684.32     321  687.61   328.8  692.03
   350.8  708.08   365.3  712.69   370.4  717.27   382.6  726.27   425.1  744.79
#Mann= 3 ,-1,0
       0      .1       0  204.48    .045       0  223.97      .1       0
Bank Sta=204.48,223.97
XS Rating Curve= 0 ,0
Exp/Cntr(USF)=0,0
Exp/Cntr=0.3,0.1

Type RM Length L Ch R = 1 ,1475    ,274.4,274.7,271
XS GIS Cut Line= 3
1612084.43608755482504.0126618851611913.03209661482747.238533488
1611887.05834555482891.683951633
#Sta/Elev= 30
       0  716.44    31.9  709.93    57.4  707.67    66.8  704.41    76.5  702.56
   113.9  688.97   133.4  678.63   144.3  676.38   160.3  665.56   168.3  663.63
     179  662.71  189.78659.2192   201.8   658.6  219.31659.2197   228.5  663.52
   231.6  664.25   244.6  663.83   268.7  664.65   290.5  666.13   311.7  669.43
   330.2     675   340.2  679.44   350.2  681.67   366.9  687.14   390.2  692.86
   406.9   695.2   420.2  699.41   426.9   702.9   433.6  707.46   444.3   717.1
#Mann= 3 ,-1,0
       0      .1       0  189.78    .045       0  219.31      .1       0
Bank Sta=189.78,219.31
XS Rating Curve= 0 ,0
Exp/Cntr(USF)=0,0
Exp/Cntr=0.3,0.1

Type RM Length L Ch R = 1 ,1200    ,296.6,300,303.4
XS GIS Cut Line= 6
1611827.22207975482385.055212677 1611786.4455865 482462.48320742
1611750.39054051482528.2402937561611702.26465251482615.898254916
1611666.20337293482681.6678084281611624.13226284482758.393704832
#Sta/Elev= 30
       0  697.43    12.7  693.56    30.4  692.68    41.5  690.61    49.5   689.8
    56.4  688.12    74.9  681.18    89.8   677.4   112.1  667.72   127.2  659.59
     153   657.3   168.3  657.26   179.8  654.04   187.1  653.09  196.49 649.697
   206.4  648.73  217.98 649.699   228.1  653.48   235.7  655.02   246.9     660
   250.7   661.1   269.4   662.4   289.4   666.1   310.5  668.51   355.4  672.41
   392.5  674.85   397.3  674.43   404.5  670.35     407  669.86     425  671.52
#Mann= 3 ,-1,0
       0      .1       0  196.49    .045       0  217.98      .1       0
Bank Sta=196.49,217.98
XS Rating Curve= 0 ,0
Exp/Cntr(USF)=0,0
Exp/Cntr=0.3,0.1