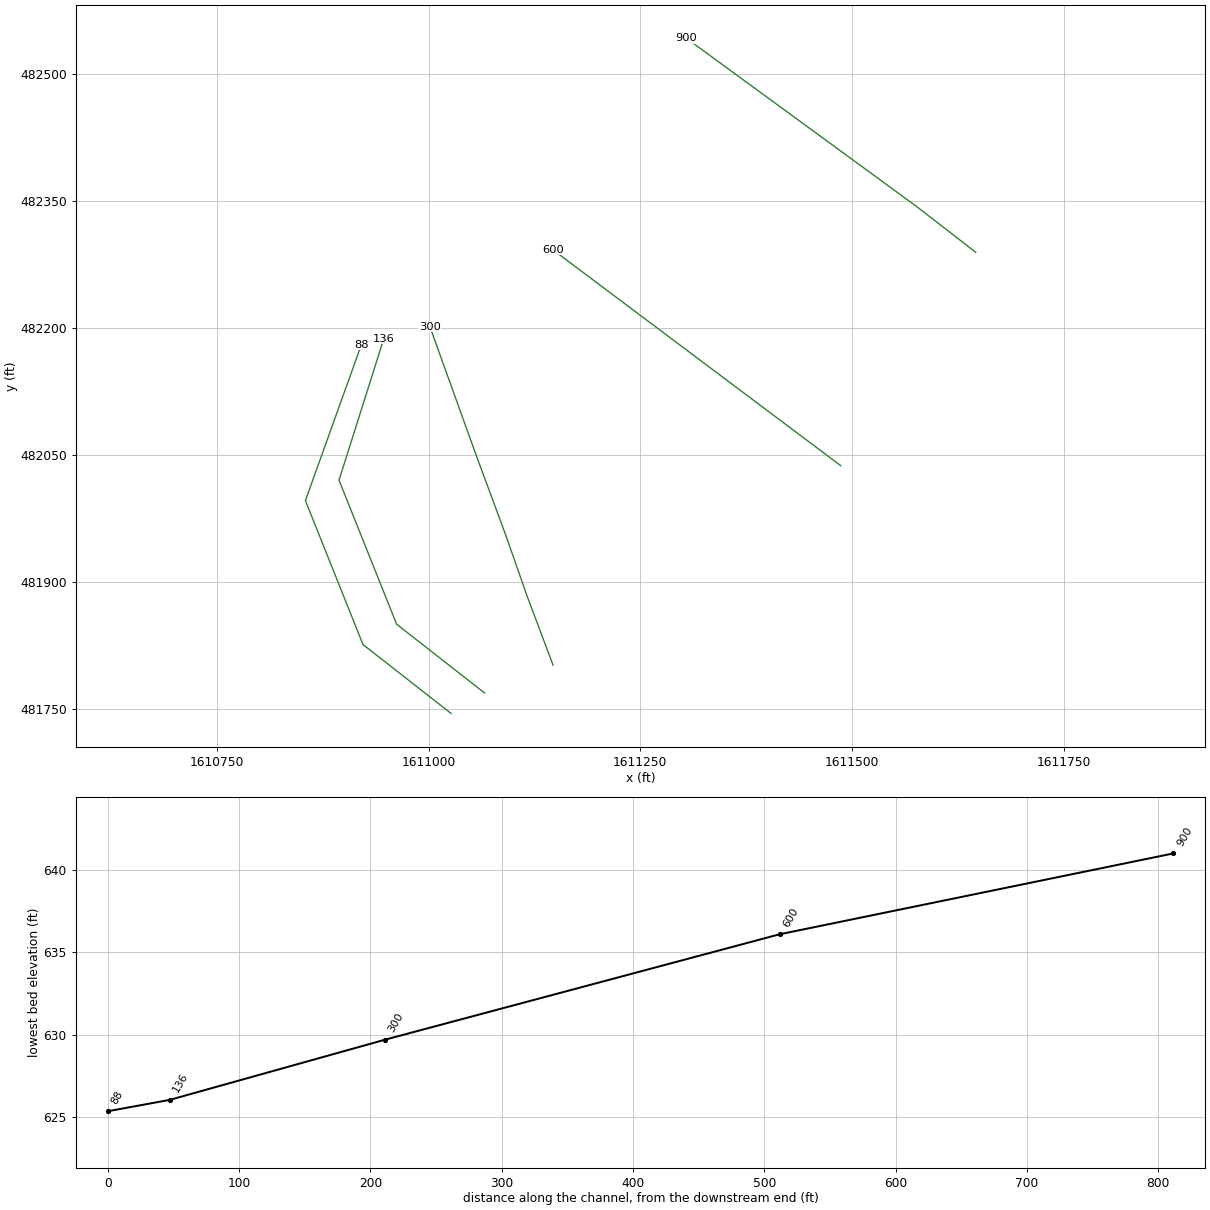
HEC-RAS study LtleTrbbCk.prj: LtleTrbbCk

--- LtleTrbbCk.g01 (geometry) --- (continued)

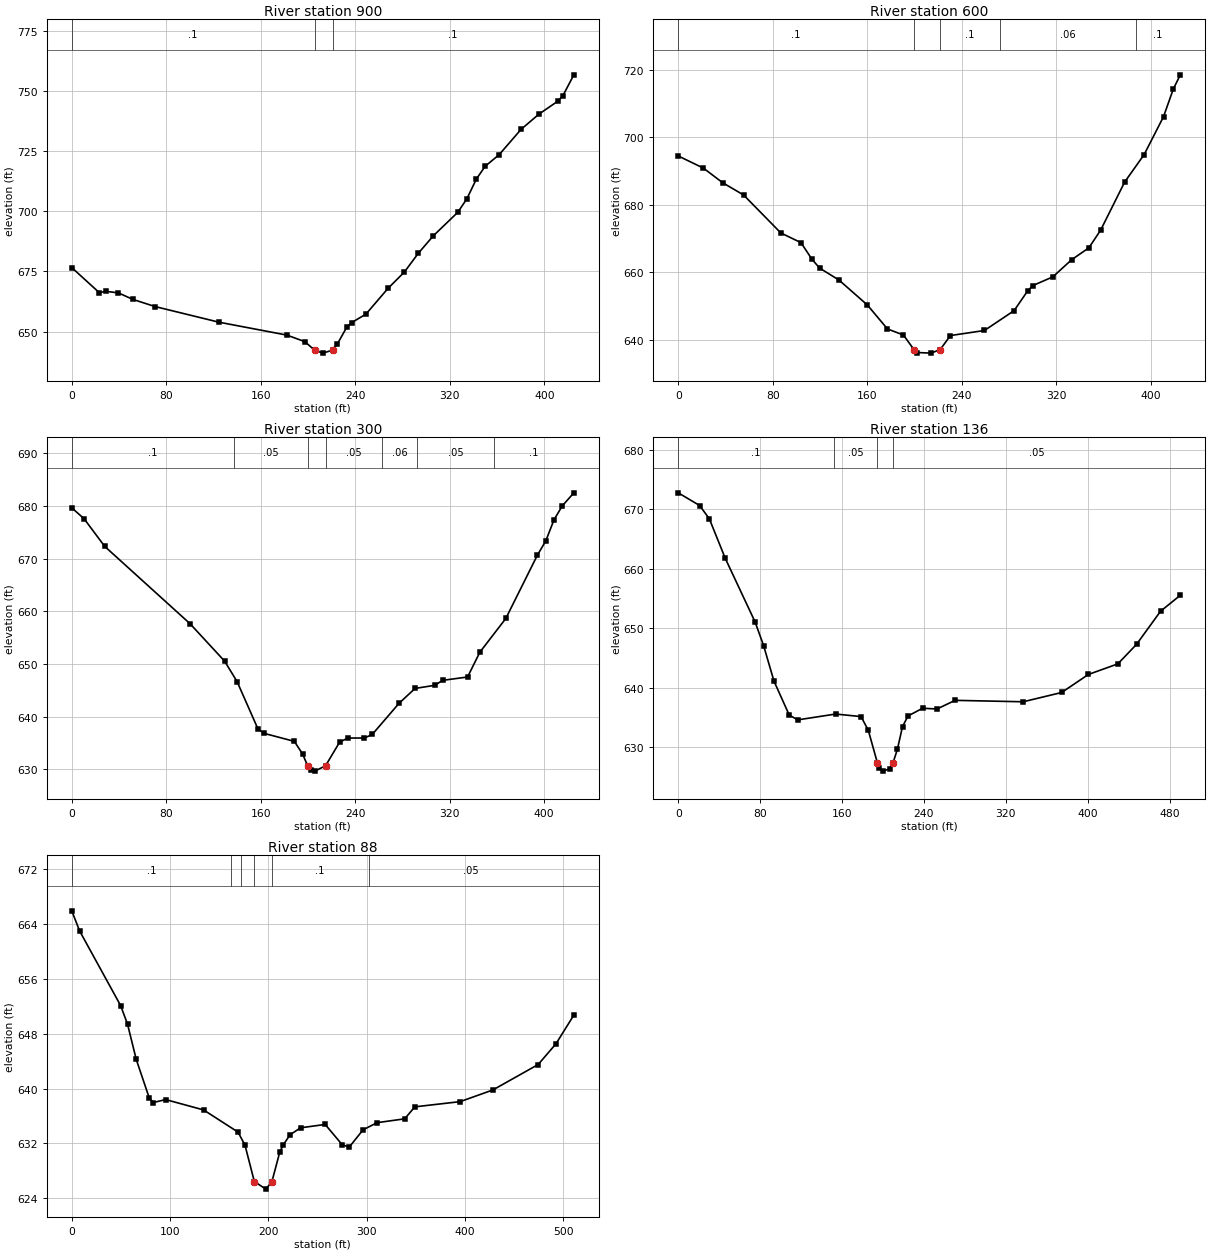
Type RM Length L Ch R = 1 ,900     ,300.5,300,299.6
XS GIS Cut Line= 6
1611646.17290117482289.4281073361611576.97750151482343.040532917
1611516.42381684482387.292412922 1611435.6848051482446.294263422
1611375.13046426482490.545815334  1611304.483952482542.172352508
#Sta/Elev= 30
       0  676.61    23.3  666.17    28.6  666.74    39.4  666.09    51.9  663.34
    70.6  660.38   124.5   653.9   182.1  648.52   197.3  645.79  205.53642.2576
   212.5  641.02  220.71642.2585   224.7  644.72   232.8  651.82   236.9  653.72
     249  657.24   267.7  667.96   281.6  674.78   293.3  682.53     306   689.8
   326.7  699.58   334.4  705.18   342.5  713.44   349.9  718.74   361.7  723.54
   380.4  734.14   395.4  740.42   411.6  745.88   415.7  748.09     425  756.79
#Mann= 3 ,-1,0
       0      .1       0  205.53    .045       0  220.71      .1       0
Bank Sta=205.53,220.71
XS Rating Curve= 0 ,0
Exp/Cntr(USF)=0,0
Exp/Cntr=0.3,0.1

Type RM Length L Ch R = 1 ,600     ,307.5,300.5,296.7
XS GIS Cut Line= 6
1611486.56692117482037.5526268331611416.56706117 482090.05252184
1611356.56718117482135.0524318371611276.56734118 482195.05296801
1611216.56746118482240.0528780071611146.56792925482292.553429171
#Sta/Elev= 30
       0  694.48    21.3  690.88    37.7  686.53    55.3  682.93    86.9  671.67
   103.9  668.81   113.2  663.89   119.7  661.27   136.1  657.73   160.1  650.35
   177.1  643.26   190.6  641.47  199.53637.1553   202.3  636.28     214   636.1
  221.75637.1539   230.4  641.31   259.2   642.8   284.3  648.68   295.9  654.58
   300.2  656.11   317.1  658.68     333  663.75   347.6  667.28   357.6  672.54
   377.9  686.76   394.4   694.9   410.8  706.12   419.1  714.32     425   718.5
#Mann= 5 ,-1,0
       0      .1       0  199.53    .045       0  221.75      .1       0
   272.5     .06       0   387.5      .1       0
Bank Sta=199.53,221.75
XS Rating Curve= 0 ,0
Exp/Cntr(USF)=0,0
Exp/Cntr=0.3,0.1

Type RM Length L Ch R = 1 ,300     ,162.8,163.9,163.1
XS GIS Cut Line= 6
1611146.92521201481801.8628095091611116.07422385481883.894797668
1611091.28752801481954.7102728341611056.56679693482048.493877918
  1611031.157727482119.0573850871611001.51769443482201.375133842
#Sta/Elev= 30
       0  679.68    10.4  677.62    27.9  672.36   100.2  657.67   129.4  650.58
     140  646.69   157.7  637.69   162.7  636.87   188.5  635.34   195.5  632.93
  199.73 630.719   202.5  629.86   205.9  629.69  214.95630.7188   226.9  635.21
   233.9  635.97   247.9  635.98   254.5  636.66   277.1  642.55   290.7  645.39
   307.3  645.98   314.2  646.93   335.2  647.56   345.6  652.27   367.6  658.68
   394.4  670.73   401.4  673.38   408.4  677.41   415.4  680.05   425.2  682.53
#Mann= 7 ,-1,0
       0      .1       0  137.64     .05       0  199.73    .045       0
  214.95     .05       0  262.67     .06       0  292.67     .05       0
  357.67      .1       0
Bank Sta=199.73,214.95
XS Rating Curve= 0 ,0
Exp/Cntr(USF)=0,0
Exp/Cntr=0.3,0.1

Type RM Length L Ch R = 1 ,136     ,48.9,47.2,48.2
XS GIS Cut Line= 4
1611066.05279825481768.9938960421610962.12857484481850.243743431
 1610894.1054468482020.3015635471610947.01232417482187.525086662
#Sta/Elev= 30
       0  672.78    20.9  670.65    30.4  668.41    45.9  661.79    75.1  651.08
    83.4  647.11    93.5  641.17   108.4  635.46   116.7  634.64   153.9  635.62
   178.6  635.19   185.7  632.88  194.58 627.403   196.3   626.5   199.8  626.03
   206.5  626.41   209.8627.4058   214.1   629.7   219.1  633.51   224.5   635.3
   238.7  636.59   252.8  636.47   270.5  637.92     337  637.68   374.6  639.24
   400.7  642.27   429.5  644.05   447.8  647.34   471.2  652.89   490.5  655.57
#Mann= 4 ,-1,0
       0      .1       0  151.92     .05       0  194.58    .045       0
   209.8     .05       0
Bank Sta=194.58,209.8
XS Rating Curve= 0 ,0
Exp/Cntr(USF)=0,0
Exp/Cntr=0.3,0.1

Type RM Length L Ch R = 1 ,88      ,,,
XS GIS Cut Line= 4
1611026.37264022481744.9023715261610922.44841682481826.152218914
1610854.42528877481996.2100390311610920.55888548482180.439344157
#Sta/Elev= 30
       0  665.96       8  663.02    49.7  652.13    56.7  649.43    65.6  644.27
    78.8  638.66      83  637.98    95.5  638.41   134.1   636.9   169.2  633.66
   176.3  631.72  185.73626.4471   197.5  625.34  203.64626.4495   211.6  630.74
   215.2  631.81   222.2  633.29   232.8  634.29   257.8  634.78   275.2  631.81
   282.3  631.48   296.4     634   310.6  635.04   338.7   635.6     349  637.35
   395.1  638.11   428.5  639.82   474.5  643.53   492.6  646.55   510.8  650.74
#Mann= 6 ,-1,0
       0      .1       0  161.92    .025       0  171.92      .1       0
  185.73    .045       0  203.64      .1       0  301.92     .05       0
Bank Sta=185.73,203.64
XS Rating Curve= 0 ,0
Exp/Cntr(USF)=0,0
Exp/Cntr=0.3,0.1
LCMann Table=0

Chan Stop Cuts=-1
Use User Specified Reach Order=0
Composite Channel Slope=5